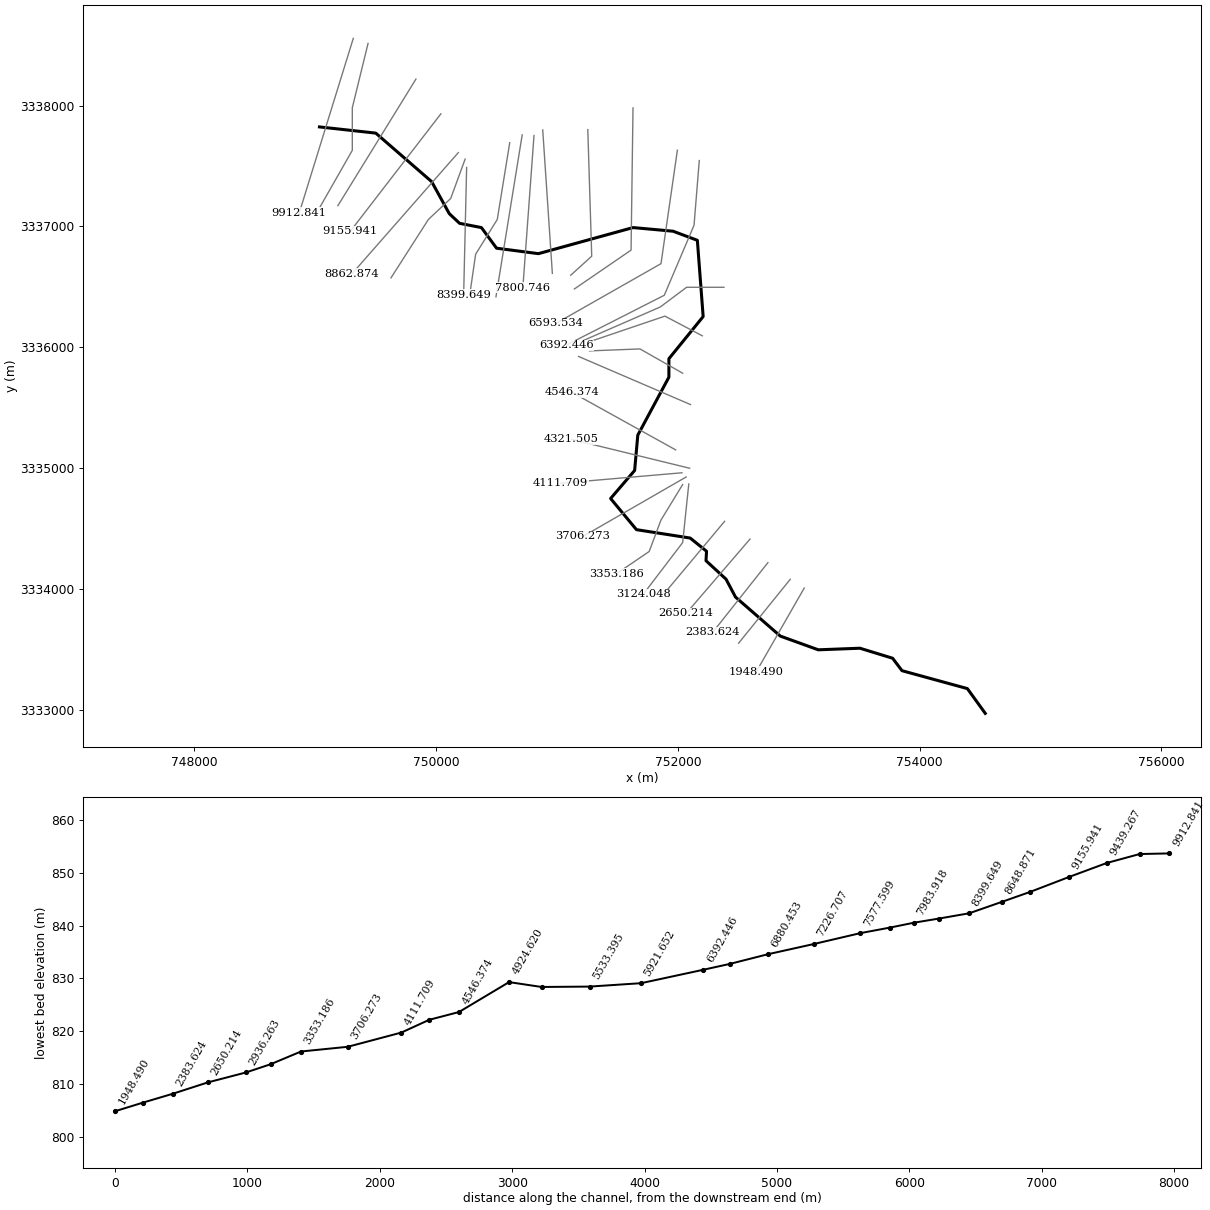
--- newStreamline.prj (project) ---

Proj Title=newStreamline
Current Plan=p01
Default Exp/Contr=0.3,0.1
SI Units
Geom File=g01
Flow File=f01
Plan File=p01
Y Axis Title=Elevation
X Axis Title(PF)=Main Channel Distance
X Axis Title(XS)=Station
BEGIN DESCRIPTION:
END DESCRIPTION:
DSS File=.\Marcelo\Sanderson.dss
DSS File=dss
DSS Export Rating Curves= 0
DSS Export Rating Curve Sorted= 0
DSS Export Volume Flow Curves= 0
DXF OffsetX= 0
DXF OffsetY= 0
DXF ScaleX= 1
DXF ScaleY= 10

--- newStreamline.p01 (plan) ---

Plan Title=Plan 01
Program Version=4.10
Geom File=g01
Flow File=f01
Subcritical Flow
K Sum by GR= 0
Std Step Tol= 0.003
Critical Tol= 0.003
Num of Std Step Trials= 20
Max Error Tol= 0.1
Flow Tol Ratio= 0.001
Split Flow NTrial= 30
Split Flow Tol= 0.006
Split Flow Ratio= 0.02
Log Output Level= 0
Friction Slope Method= 1
Unsteady Friction Slope Method= 2
Unsteady Bridges Friction Slope Method= 1
Parabolic Critical Depth
Global Vel Dist= 0 , 0 , 0
Global Log Level= 0
CheckData=True
Encroach Param=-1 ,0,0, 0
Computation Interval=1HOUR
Output Interval=1HOUR
Run HTab= 0
Run UNet= 0
Run PostProcess= 0
Run WQNet= 0
UNET Theta= 1
UNET Theta Warmup= 1
UNET ZTol= 0.006
UNET ZSATol= 0.015
UNET MxIter= 20
UNET MaxInSteps= 0
UNET DtIC= 0
UNET DtMin= 0
UNET MaxCRTS= 20
UNET WFStab= 2
UNET SFStab= 1
UNET WFX= 1
UNET SFX= 1
UNET DSS MLevel= 4
UNET DZMax Abort= 30.48
UNET Convert EG Bridges= 0
UNET Use Existing IB Tables=-1
UNET Froude Reduction=False
UNET Froude Limit= 1
UNET Froude Power= 10
UNET Time Slicing=0,0, 5
UNET Junction Losses=0
Instantaneous Interval=1HOUR
Write IC File= 0
Write IC File at Sim End=0
Echo Input=False
Echo Parameters=False
Echo Output=False
Write Detailed= 0
WQ AD Non Conservative
WQ ULTIMATE=-1
WQ Max Comp Step=1HOUR
WQ Output Interval=15MIN
WQ Output Selected Increments= 0
WQ Output face flow=0
WQ Output face velocity=0
WQ Output face area=0
WQ Output face dispersion=0
WQ Output cell volume=0
WQ Output cell surface area=0
WQ Output cell continuity=0
WQ Output cumulative cell continuity=0
WQ Output face conc=0
WQ Output face dconc_dx=0
WQ Output face courant=0
WQ Output face peclet=0
WQ Output face adv mass=0
WQ Output face disp mass=0
WQ Output cell mass=0
WQ Output cell source sink temp=0
WQ Output cell source sink nsm=0
WQ Output MaxMinRange=-1
WQ Daily Max Min Mean=-1
WQ Daily Range=0
WQ Daily Time=0
WQ Create Restart=0
WQ Fixed Restart=0
WQ System Summary=0
WQ Use Fixed Temperature=0
Sorting and Armoring Iterations= 10
XS Update Threshold= 0.02
Hydraulics Update Threshold= 0.02
Energy Slope Method= 1
Volume Change Method= 0
XS Weighting Method= 0
Number of US Weighted Cross Sections= 1
Number of DS Weighted Cross Sections= 1
Upstream XS Weight=0.25
Main XS Weight=0.5
Downstream XS Weight=0.25
Number of DS XS's Weighted with US Boundary= 1
Upstream Boundary Weight= 1
Weight of XSs Associated with US Boundary= 0
Number of US XS's Weighted with DS Boundary= 1
Downstream Boundary Weight= 0.5
Weight of XSs Associated with DS Boundary= 0.5
Sediment Output Level= 4
Mass or Volume Output= 0
Output Increment Type= 1
Profile and TS Output Increment= 10
XS Output Flag= 0
XS Output Increment= 10
Disregard all LS=0
Disregard all Conn=0
Disregard all Breaches=0
Disregard all Pumps=0

--- newStreamline.f01 (steady flow) ---

Flow Title=steadyflow
Program Version=4.10
Number of Profiles= 8
Profile Names=PF 1,PF 2,PF 3,PF 4,PF 5,PF 6,PF 7,PF 8
River Rch & RM=SandersonCreek2,SandersonCreek2 ,9912.841
2831.6851223.684454.2872374.3487321.764382.23212756.9376 246.838
Boundary for River Rch & Prof#=SandersonCreek2,SandersonCreek2 , 1
Up Type= 0
Dn Type= 3
Dn Slope=0.007
DSS Import GetInterval= 0
DSS Import GetPeak= 0
DSS Import FillOption= 0

--- newStreamline.g01 (geometry) ---

Geom Title=geometryNew
Program Version=4.10

River Reach=SandersonCreek2 ,SandersonCreek2
Reach XY= 30
       749035.15      3337823.42       749500.78      3337772.12
       749963.03      3337370.92       750108.82      3337106.08
       750194.13      3337025.78       750374.79      3336990.66
       750500.25      3336820.04       750846.51      3336774.87
       751629.36      3336990.66       751960.56      3336960.55
       752161.29      3336885.27        752209.3      3336254.55
       751925.85      3335905.68       751925.85      3335753.05
       751668.56      3335273.36       751642.39      3334981.18
       751443.71       3334749.3       751657.46      3334491.56
       752102.02      3334422.12       752237.21       3334313.1
       752232.85      3334234.61       752398.56      3334081.98
       752477.06      3333933.71       752847.73      3333611.01
       753161.71      3333497.62       753506.21      3333510.71
       753776.59      3333427.85       753854.21      3333324.93
       754394.95      3333176.67       754543.22      3332971.71

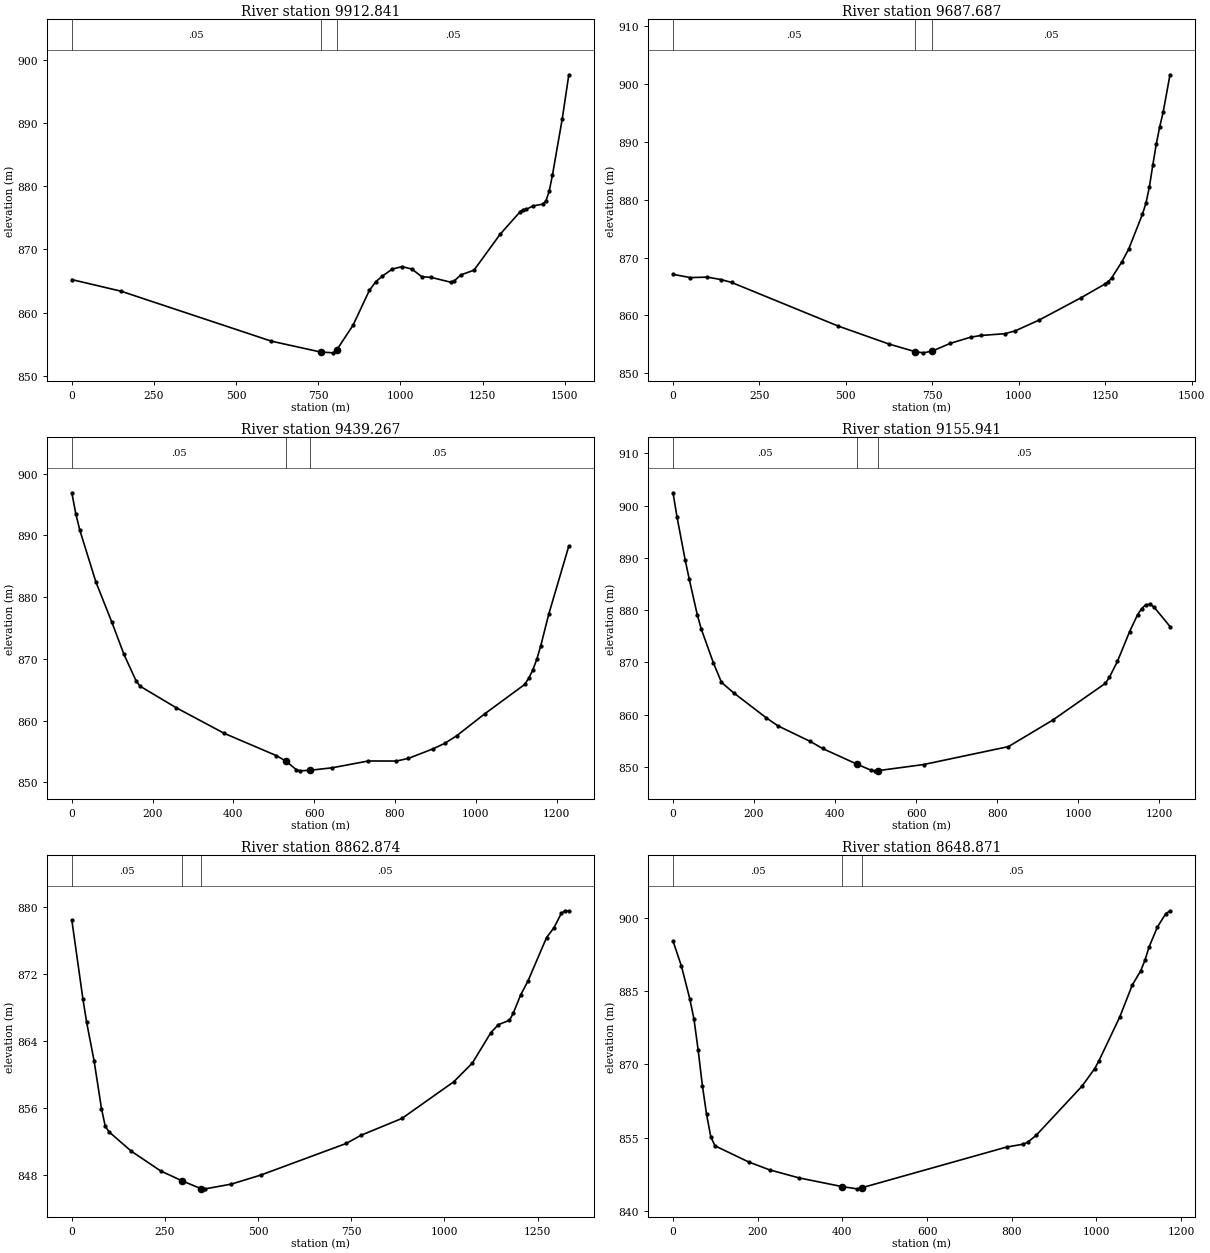
Type RM Length L Ch R = 1 ,9912.841,225.1539,225.1539,225.1539
XS GIS Cut Line= 2
       749314.96      3338556.19       748867.72      3337111.25
#Sta/Elev= 30
       0865.2352 149.267863.4122607.0181855.5129756.8909853.7951796.0892853.6641
806.9571 854.181855.7961858.0151 905.551 863.531925.4529864.9249945.3561865.7969
975.2091866.89811005.062867.29411034.916 866.8991064.769 865.7141094.623865.5741
 1154.33864.80991164.281865.05991184.183865.98491223.988 866.7261303.597 872.405
1363.304875.89621373.256 876.2831383.207876.33811403.109876.86391432.963 877.166
1442.914877.67191452.865879.19411462.816881.7681 1492.67890.66091512.572897.6031
#Mann= 3 , 0 , 0
       0     .05       0756.8909     .03       0806.9571     .05       0
Bank Sta=756.8909,806.9571
XS Rating Curve= 0 ,0
Exp/Cntr=0.3,0.1

Type RM Length L Ch R = 1 ,9687.687,248.4199,248.4199,248.4199
XS GIS Cut Line= 4
       749437.06      3338514.29       749306.82       3337982.5
       749306.82      3337629.78       749040.93      3337163.11
#Sta/Elev= 30
       0867.1082 49.7729 866.543 99.5459866.6241 139.364866.1971 169.228865.7079
  477.82858.1699 625.884 855.039 699.402853.7662  723.86 853.546 749.277 853.842
802.2422855.1911 861.028856.2509890.4211856.5419959.8969 856.855989.7362857.3412
 1059.36859.22391178.717863.01711248.342865.39921258.288865.79781268.235866.4532
1298.074 869.2491317.967871.47111357.753 877.5071367.699879.38091377.645882.1729
1387.592885.97011397.538 889.5741407.485 892.5551417.431895.08211437.324901.5731
#Mann= 3 , 0 , 0
       0     .05       0 699.402     .03       0 749.277     .05       0
Bank Sta=699.402,749.277
XS Rating Curve= 0 ,0
Exp/Cntr=0.3,0.1

Type RM Length L Ch R = 1 ,9439.267,283.3259,283.3259,283.3259
XS GIS Cut Line= 2
       749833.18      3338219.09       749187.44      3337171.79
#Sta/Elev= 30
       0 896.923  9.9218893.4678 19.8449890.8481 59.5341882.4731 99.2231875.9211
128.9901 870.741158.7569866.4769  168.68865.5829257.9809862.0951377.0489 857.937
 506.039854.3251530.2901853.4199 555.651  852.04565.5729851.8499 588.856 851.934
644.9519852.3491 734.254853.4501  803.71 853.436833.4771853.8741893.0109855.3831
922.7789856.2899 952.546857.52311022.002861.08111121.226865.85691131.148 866.871
 1141.07  868.171150.993869.91291160.915872.1301 1180.76877.25491230.372888.2842
#Mann= 3 , 0 , 0
       0     .05       0530.2901     .03       0 588.856     .05       0
Bank Sta=530.2901,588.856
XS Rating Curve= 0 ,0
Exp/Cntr=0.3,0.1

Type RM Length L Ch R = 1 ,9155.941,293.067,293.067,293.067
XS GIS Cut Line= 2
       750039.39      3337931.49       749290.54      3336960.16
#Sta/Elev= 30
       0902.4479  9.9709897.7771  29.914889.6249 39.8849885.9829  59.828879.1099
 69.7989876.3539 99.7129 869.876119.6559866.1498149.5699864.1558 229.341859.4141
259.2549857.8151 339.026 854.835  368.94 853.497455.1451 850.452488.5959849.3401
498.5671849.2161505.5529849.2468 618.224  850.42827.6219853.8491937.3079858.9392
1066.935865.96211076.906 867.1211096.849870.17991126.763 875.8691146.706 879.145
1156.677 880.2811166.648881.0049 1176.62881.09781186.591 880.6191226.476876.8481
#Mann= 3 , 0 , 0
       0     .05       0455.1451     .03       0505.5529     .05       0
Bank Sta=455.1451,505.5529
XS Rating Curve= 0 ,0
Exp/Cntr=0.3,0.1

Type RM Length L Ch R = 1 ,8862.874,214.0031,214.0031,214.0031
XS GIS Cut Line= 2
       750183.72      3337610.67       749303.98      3336608.07
#Sta/Elev= 30
       0878.3952 29.8619 868.955 39.8169 866.212 59.7249861.6348  79.633855.9421
 89.5871853.8701  99.541853.1941159.2659850.8848238.8989848.5129295.3149847.3589
346.5351846.4189358.3491 846.394428.0279846.9569507.6609848.0411736.6071851.7999
776.4232 852.777885.9189 854.7751025.277859.14711075.048861.37481124.818 864.999
1144.726865.93991174.589866.46191184.543867.27611204.451  869.471224.359871.1479
 1274.13876.30911294.038877.47991313.946 879.209  1323.9879.49791333.854 879.494
#Mann= 3 , 0 , 0
       0     .05       0295.3149     .03       0346.5351     .05       0
Bank Sta=295.3149,346.5351
XS Rating Curve= 0 ,0
Exp/Cntr=0.3,0.1

Type RM Length L Ch R = 1 ,8648.871,249.2218,249.2218,249.2218
XS GIS Cut Line= 4
       750240.16      3337557.07       750120.78      3337231.48
       749936.29      3337057.84       749626.98      3336574.89
#Sta/Elev= 30
       0895.1988  19.816  890.09 39.6319 883.379 49.5401879.2221 59.4479872.8481
  69.356865.6359 79.2638 859.731  89.172855.1661 99.0801853.3062 178.344850.0089
 227.884848.3889 297.241846.7481399.7449 844.951434.4829844.4999446.3391844.7319
 788.015853.0568827.5679853.6421 837.456854.0319 857.232 855.416965.9999865.5219
995.6649869.07591005.553870.64811054.993879.65311084.657 886.2131104.433889.0922
1114.321891.22081124.209893.97111143.985898.08681163.762900.8041 1173.65 901.392
#Mann= 3 , 0 , 0
       0     .05       0399.7449     .03       0446.3391     .05       0
Bank Sta=399.7449,446.3391
XS Rating Curve= 0 ,0
Exp/Cntr=0.3,0.1

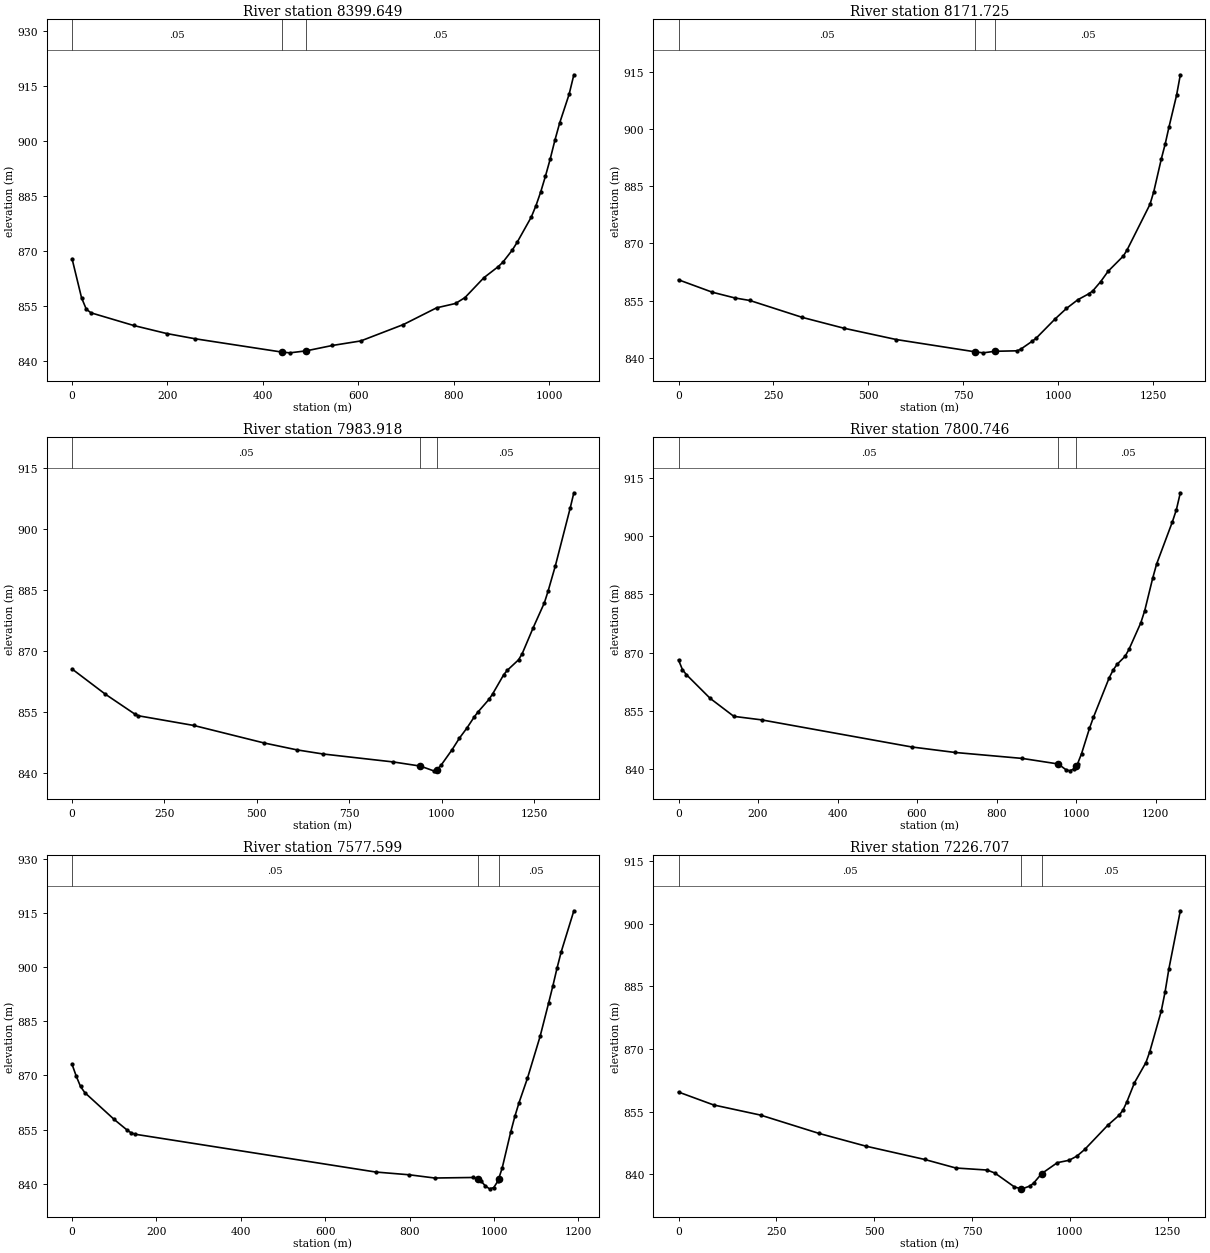
Type RM Length L Ch R = 1 ,8399.649,227.924,227.924,227.924
XS GIS Cut Line= 2
       750252.53      3337487.81       750227.95      3336436.05
#Sta/Elev= 30
       0867.9219 19.8501857.3162  29.775854.2029 39.6999853.2089 129.024849.7668
198.4989 847.572258.0479 846.147 439.859842.5278456.5471  842.32490.8831842.8619
545.8709844.3289605.4209 845.563694.7449850.0259764.2198854.5699803.9191 855.754
 823.769  857.36863.4692 862.776893.2441 865.757903.1691866.9819923.0192870.3049
932.9431872.3589962.7181879.2568 972.643 882.396982.5679886.1231992.4928890.4199
1002.418895.06021012.343 900.2141022.268904.87291042.118912.69891052.043918.0009
#Mann= 3 , 0 , 0
       0     .05       0 439.859     .03       0490.8831     .05       0
Bank Sta=439.859,490.8831
XS Rating Curve= 0 ,0
Exp/Cntr=0.3,0.1

Type RM Length L Ch R = 1 ,8171.725,187.8071,187.8071,187.8071
XS GIS Cut Line= 4
       750609.16      3337692.73       750506.06      3337057.84
       750326.99      3336770.24       750278.15       3336433.8
#Sta/Elev= 30
       0860.4501 89.0589 857.197148.4321855.6979188.0141855.0319326.5511850.5911
 435.401847.7802573.9381844.8019 781.676 841.583802.6381841.3239833.3649841.7311
892.3179 841.857 902.283 842.338 932.176 844.395942.1411845.1598991.9981850.1921
1021.994 852.9551051.991855.23321081.988 856.8481091.987 857.6211111.984859.9512
1131.982 862.7161171.978866.69091181.977868.3289 1241.97 880.1991251.969883.5131
1271.967892.14011281.966895.95811291.965900.40911311.963 908.7351321.961914.1422
#Mann= 3 , 0 , 0
       0     .05       0 781.676     .03       0833.3649     .05       0
Bank Sta=781.676,833.3649
XS Rating Curve= 0 ,0
Exp/Cntr=0.3,0.1

Type RM Length L Ch R = 1 ,7983.918,183.172,183.172,183.172
XS GIS Cut Line= 2
       750712.26      3337757.85       750495.21      3336417.52
#Sta/Elev= 30
       0865.5829 89.8529859.4009 169.723 854.504 179.707854.0779 329.462851.6968
519.1531847.4031 609.006 845.688 678.892844.6871868.5818842.7339942.2999841.7131
978.4031840.5421987.3792840.8481998.3699  841.911028.321 845.7451048.289848.6031
1068.256 851.0471088.223853.79381098.207855.00091128.158 858.1151138.141 859.475
1168.092 864.1941178.076   865.31208.027867.83511218.011869.35611247.962875.7779
1277.912881.84091287.896884.68291307.863 890.9991347.798905.12591357.782908.9108
#Mann= 3 , 0 , 0
       0     .05       0942.2999     .03       0987.3792     .05       0
Bank Sta=942.2999,987.3792
XS Rating Curve= 0 ,0
Exp/Cntr=0.3,0.1

Type RM Length L Ch R = 1 ,7800.746,223.1471,223.1471,223.1471
XS GIS Cut Line= 2
       750809.94      3337752.42       750717.69      3336493.49
#Sta/Elev= 30
       0  868.11  9.9389 865.614 19.8791864.3351  79.515858.2509 139.151 853.618
 208.727 852.721 586.424845.7508695.7569844.3329864.7271842.8018955.3091841.3729
974.0601839.9279 983.999839.6091993.9391  840.08  1000.5 840.9781003.878 841.441
1013.818844.02411033.696 850.5131043.636853.35191083.393 863.5491093.332 865.532
1103.272867.0091 1123.15 869.029 1133.09870.84111162.908 877.6781172.847880.8431
1192.726 889.1291202.665892.80921242.422903.68411252.362906.75991262.301911.1219
#Mann= 3 , 0 , 0
       0     .05       0955.3091     .03       0  1000.5     .05       0
Bank Sta=955.3091,1000.5
XS Rating Curve= 0 ,0
Exp/Cntr=0.3,0.1

Type RM Length L Ch R = 1 ,7577.599,350.8931,350.8931,350.8931
XS GIS Cut Line= 2
       750882.11      3337798.24        750961.7      3336611.67
#Sta/Elev= 30
       0873.0621  9.9941869.7612  19.987866.9438  29.981865.2519  99.936857.7792
 129.917854.9009139.9111 854.088 149.904853.6851719.5402  843.22799.4889842.4489
859.4501841.5592 949.392 841.704961.8571 841.308969.3802840.6829 979.373839.3829
989.3671 838.559999.3599 838.9081009.354840.74691010.735841.23881019.348844.3118
1039.335854.17911049.328858.61211059.322862.44891079.309 869.235 1109.29 880.832
1129.278 890.0061139.271894.70421149.265899.68611159.259 904.259 1189.24915.6329
#Mann= 3 , 0 , 0
       0     .05       0961.8571     .03       01010.735     .05       0
Bank Sta=961.8571,1010.735
XS Rating Curve= 0 ,0
Exp/Cntr=0.3,0.1

Type RM Length L Ch R = 1 ,7226.707,346.2531,346.2531,346.2531
XS GIS Cut Line= 3
        751254.9      3337801.26       751287.46      3336753.96
       751113.82       3336596.6
#Sta/Elev= 30
       0 859.679 89.8121856.5862209.5601 854.162359.2461849.7668 478.995846.7161
628.6811843.5419 708.514841.4921 788.346841.0021 808.304840.2882858.2001836.9579
 874.936836.5172 878.158 836.501 898.116 837.188908.0949837.9531 927.888 840.151
967.9689842.7711997.9069 843.3381017.865844.33811037.823845.93011096.623851.7151
1125.916854.14111135.681855.35691145.445857.30911164.973861.90491194.266866.7549
1204.031 869.3211233.323 879.0451243.088883.60391252.852889.15411282.145903.0901
#Mann= 3 , 0 , 0
       0     .05       0 874.936     .03       0 927.888     .05       0
Bank Sta=874.936,927.888
XS Rating Curve= 0 ,0
Exp/Cntr=0.3,0.1

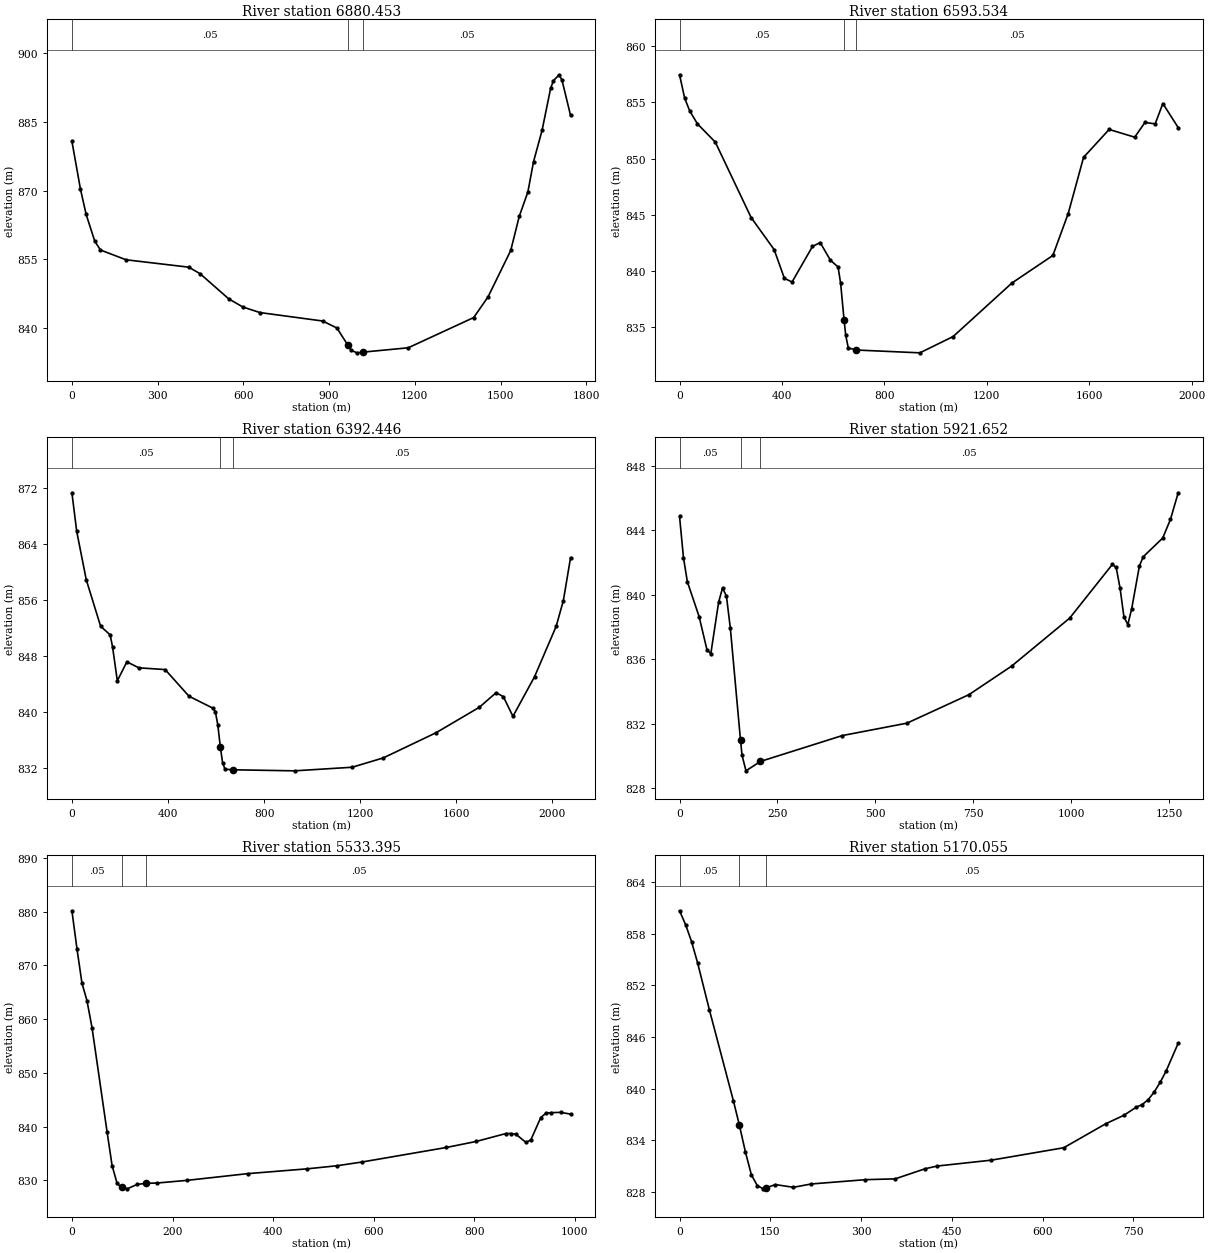
Type RM Length L Ch R = 1 ,6880.453,286.9189,286.9189,286.9189
XS GIS Cut Line= 3
       751628.94      3337980.73       751612.86      3336804.13
       751144.18      3336483.04
#Sta/Elev= 30
       0880.7939 29.9161870.3259  49.861864.8011 79.7771859.0011  99.722857.0409
 189.471854.9022 408.859853.2861 448.747 851.845 548.469846.3768  598.33844.5789
658.1628 843.366877.5509 841.522 927.411839.9831965.2401 836.267 977.272 835.138
997.2169834.56891018.457834.72411176.716 835.6721405.955842.28091455.789846.7661
1535.525 856.9371565.426864.42291595.326 869.681 1615.26876.33591645.161883.1931
1675.062 892.3731685.029894.06491704.962 895.3251714.929 894.129 1744.83886.4371
#Mann= 3 , 0 , 0
       0     .05       0965.2401     .03       01018.457     .05       0
Bank Sta=965.2401,1018.457
XS Rating Curve= 0 ,0
Exp/Cntr=0.3,0.1

Type RM Length L Ch R = 1 ,6593.534,201.0881,201.0881,201.0881
XS GIS Cut Line= 3
       751996.15      3337630.87       751860.49       3336692.1
       750992.26       3336198.3
#Sta/Elev= 30
       0 857.438  19.969 855.359 39.9379854.2178 69.8909853.0809139.7819851.4509
279.5641844.7568369.4231841.9119 409.361839.3619 439.314  839.03 519.189842.1889
549.1429 842.537  589.08840.9709619.0339 840.369629.0179838.9279642.6251835.6339
648.9868834.3001658.9709833.1791690.5302832.9919938.5359832.7419 1068.38834.1891
 1298.11838.94491457.922841.39221517.852845.11721577.782 850.1031677.665 852.582
1777.547851.89591817.501853.20591857.454853.07791887.419854.88591947.348852.7469
#Mann= 3 , 0 , 0
       0     .05       0642.6251     .03       0690.5302     .05       0
Bank Sta=642.6251,690.5302
XS Rating Curve= 0 ,0
Exp/Cntr=0.3,0.1

Type RM Length L Ch R = 1 ,6392.446,470.7941,470.7941,470.7941
XS GIS Cut Line= 4
       752177.21      3337545.01        752133.8      3337009.61
        751887.8      3336430.79       751077.46      3336018.38
#Sta/Elev= 30
       0871.3439 19.8949 865.845  59.685858.9249119.3691852.2878159.1589 851.048
 169.107 849.334189.0019 844.492228.7911 847.194 278.529846.3421 387.951846.0919
487.4249 842.284587.0771 840.572597.0599840.0681 607.043 838.215618.0329834.9719
627.0081832.8129636.9908 831.858 669.086831.7791 926.496 831.6271166.086  832.14
1295.978833.47411515.795837.07291695.646840.70511765.588 842.7931795.563842.2209
1835.529839.41611925.455 845.072 2015.38852.26282045.355855.9488 2075.33862.0842
#Mann= 3 , 0 , 0
       0     .05       0618.0329     .03       0 669.086     .05       0
Bank Sta=618.0329,669.086
XS Rating Curve= 0 ,0
Exp/Cntr=0.3,0.1

Type RM Length L Ch R = 1 ,5921.652,388.2561,388.2561,388.2561
XS GIS Cut Line= 4
       752381.42      3336496.75       752072.12      3336496.75
       751855.06      3336333.96       751220.17      3336057.21
#Sta/Elev= 30
       0844.8441  9.9779 842.298  19.955840.7969 49.8881838.6441 69.8431 836.598
  79.821 836.334  99.776 839.532 109.753840.4141119.7309839.9069129.7089837.9172
155.7129830.9631159.6411 830.038169.6191 829.081206.3871829.6628 415.895831.2689
580.6251832.0348  738.93833.8011 847.764 835.569996.1751 838.5451105.009 841.871
1114.903841.68111124.797840.39611134.692838.61691144.586838.1439 1154.48839.1291
1174.268841.78691184.162842.35291233.632843.5051 1253.42  844.661273.208 846.311
#Mann= 3 , 0 , 0
       0     .05       0155.7129     .03       0206.3871     .05       0
Bank Sta=155.7129,206.3871
XS Rating Curve= 0 ,0
Exp/Cntr=0.3,0.1

Type RM Length L Ch R = 1 ,5533.395,363.3411,363.3411,363.3411
XS GIS Cut Line= 3
       752202.35       3336095.2       751893.05      3336257.99
       751285.29      3336051.78
#Sta/Elev= 30
       0880.1371  9.9871873.1091 19.9729866.6939   29.96 863.403 39.9459858.4229
 69.9059839.0229  79.892832.7581 89.8791829.4321 98.7351828.7341109.8521 828.437
 129.825829.2669 148.003829.4659169.7709829.5211229.6909 830.021  349.53831.2639
468.0131832.1601527.2549 832.731 576.623833.4241 744.474836.1271803.7161837.2481
862.9571838.7239872.8311838.7261882.7039838.5831902.4521837.0781912.3249837.5231
 932.072841.6979 941.946 842.466  951.82842.6041 971.567842.6541991.3141842.3331
#Mann= 3 , 0 , 0
       0     .05       0 98.7351     .03       0 148.003     .05       0
Bank Sta=98.7351,148.003
XS Rating Curve= 0 ,0
Exp/Cntr=0.3,0.1

Type RM Length L Ch R = 1 ,5170.055,245.435,245.435,245.435
XS GIS Cut Line= 3
       752039.56      3335785.89       751686.84      3335986.67
       751269.01      3335970.39
#Sta/Elev= 30
       0860.6689   9.899 859.073  19.798 857.097  29.697 854.655 49.4949849.1069
 89.0909838.5651 98.8811835.7601108.8889832.6319 118.787829.9749128.6859828.7259
138.5849828.3641142.8829 828.479158.3829828.8579188.0799828.5439217.7769828.9301
306.8681829.4279356.3621 829.526405.8571830.6989 425.769831.0131515.3729 831.698
634.8442833.1379704.5361835.9351734.4031836.9149754.3151 837.833764.2711 838.153
774.2271838.7029 784.183 839.595 794.139840.7249 804.095  842.06 824.007 845.283
#Mann= 3 , 0 , 0
       0     .05       0 98.8811     .03       0142.8829     .05       0
Bank Sta=98.8811,142.8829
XS Rating Curve= 0 ,0
Exp/Cntr=0.3,0.1

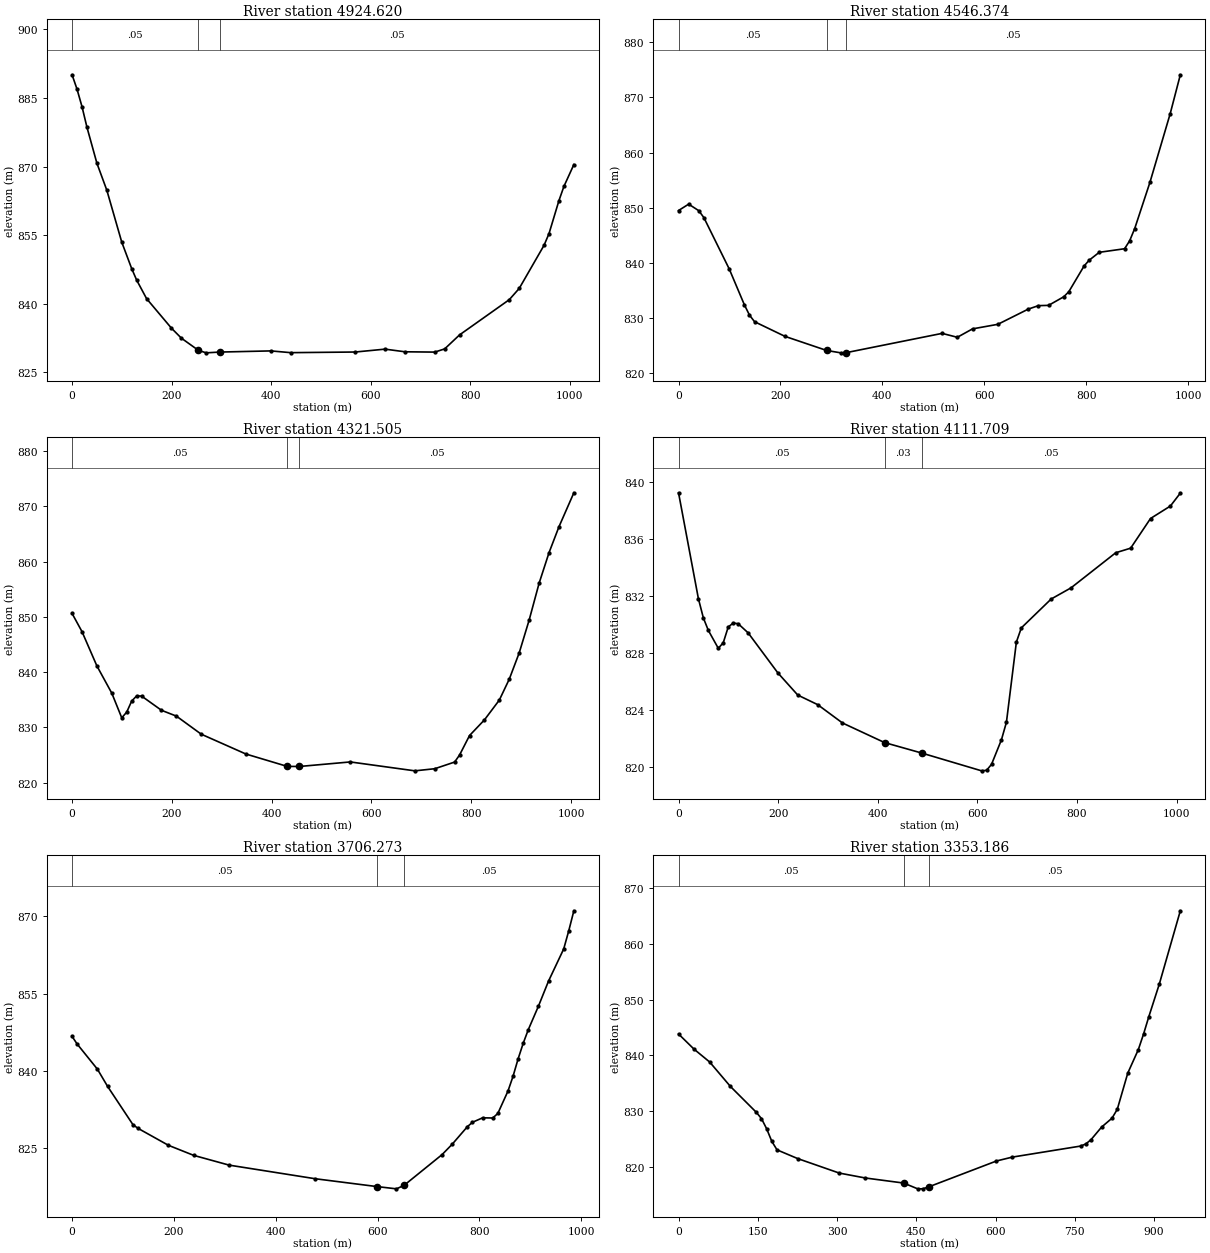
Type RM Length L Ch R = 1 ,4924.620,378.2461,378.2461,378.2461
XS GIS Cut Line= 2
       752104.86      3335526.39       751178.75      3335924.32
#Sta/Elev= 30
       0 890.058  9.9801886.9019 19.9601883.0891 29.9399878.5729    49.9870.7219
 69.8599864.8139 99.8001853.4821119.7599 847.693129.7399 845.186149.7001841.1261
199.6001834.6799219.5599 832.492253.9109 829.821  269.46829.2849 296.952829.4559
399.1999829.7079439.1211829.3251568.8611829.4642628.7411 830.093668.6611829.5151
728.5421 829.447 748.502830.1481778.4421833.2111878.2419840.9039 898.202843.3599
948.1021852.7889958.0818855.3489978.0428862.5682988.0229865.66311007.983870.4329
#Mann= 3 , 0 , 0
       0     .05       0253.9109     .03       0 296.952     .05       0
Bank Sta=253.9109,296.952
XS Rating Curve= 0 ,0
Exp/Cntr=0.3,0.1

Type RM Length L Ch R = 1 ,4546.374,224.8689,224.8689,224.8689
XS GIS Cut Line= 2
       751981.86       3335151.6       751120.87      3335629.13
#Sta/Elev= 30
       0  849.47   19.89850.6261 39.7801849.4349 49.7251848.1819 99.4489838.8611
 129.284 832.321 139.229 830.466 149.174829.2709208.8429826.6112 290.539824.0512
318.2371 823.618328.9371 823.651517.1359827.1541  546.97826.4438576.8051827.9709
626.5289828.7999 686.199831.5612706.0881832.1899725.9781832.2399755.8129833.8011
765.7579834.7201 795.592839.3781 805.537840.4312825.4271 841.878875.1509 842.527
885.0959843.9659 895.041846.1918 924.876854.5751964.6551867.0561984.5452874.1271
#Mann= 3 , 0 , 0
       0     .05       0 290.539     .03       0328.9371     .05       0
Bank Sta=290.539,328.9371
XS Rating Curve= 0 ,0
Exp/Cntr=0.3,0.1

Type RM Length L Ch R = 1 ,4321.505,209.7951,209.7951,209.7951
XS GIS Cut Line= 2
       752097.62      3334999.67       751120.87      3335238.43
#Sta/Elev= 30
       0850.6151 19.9111847.3199 49.7781841.1129 79.6439836.1859 99.5559831.7349
 109.511832.7678 119.467834.7618 129.422835.6988 139.378835.6641179.2001 833.094
209.0669832.0422258.8441828.7731348.4449825.1841431.2639 822.946455.6979 822.935
557.5109823.7549686.9338 822.145 726.756822.5269766.5781823.7339776.5341825.0159
796.4451 828.529826.3119831.3609 856.178834.9468  876.09  838.73 896.001843.4819
915.9121 849.413935.8228 856.064955.7339 861.601 975.645 866.2911005.512872.4379
#Mann= 3 , 0 , 0
       0     .05       0431.2639     .03       0455.6979     .05       0
Bank Sta=431.2639,455.6979
XS Rating Curve= 0 ,0
Exp/Cntr=0.3,0.1

Type RM Length L Ch R = 1 ,4111.709,405.4361,405.4361,405.4361
XS GIS Cut Line= 2
       752034.13      3334962.16       751030.25      3334875.34
#Sta/Elev= 30
       0 839.264 39.9059831.8239  49.883830.4709 59.8591829.5961 79.8119828.3419
 89.7889828.7271 99.7659 829.836 109.742830.1122 119.719830.0679139.6719829.4279
199.5309826.6082239.4369825.0549 279.344 824.384 329.226 823.095 413.734 821.718
   488.4820.9819608.5701819.7331618.5471  819.77628.5229 820.189 648.476 821.921
658.4531 823.149678.4058 828.778688.3829 829.775748.2419831.8011788.1479832.5859
877.9371835.0521907.8669 835.373947.7728837.4569  987.68838.33291007.633  839.24
#Mann= 3 , 0 , 0
       0     .05       0 413.734     .03       0   488.4     .05       0
Bank Sta=413.734,488.4
XS Rating Curve= 0 ,0
Exp/Cntr=0.3,0.1

Type RM Length L Ch R = 1 ,3706.273,353.087,353.087,353.087
XS GIS Cut Line= 2
       752068.68      3334927.31       751214.93      3334435.32
#Sta/Elev= 30
       0 846.664  9.9529845.1842 49.7659840.2922  69.673836.9589119.4389829.5229
129.3919828.7969 189.111825.4999238.8782 823.536  308.55 821.639477.7551818.9921
 598.416817.4748 637.007 817.032651.9221817.7071726.5868 823.686 746.493825.7051
776.3531 829.124 786.306829.9741 806.213830.8378 826.119830.8028836.0722831.6879
 855.979836.0359865.9319838.9028875.8848842.2928 885.839845.3061895.7919 847.949
915.6982852.5131 935.605 857.413 965.465863.6722975.4179  867.22985.3708871.0831
#Mann= 3 , 0 , 0
       0     .05       0 598.416     .03       0651.9221     .05       0
Bank Sta=598.416,651.9221
XS Rating Curve= 0 ,0
Exp/Cntr=0.3,0.1

Type RM Length L Ch R = 1 ,3353.186,229.138,229.138,229.138
XS GIS Cut Line= 4
       752039.56      3334864.49       751860.49      3334571.46
       751762.81      3334310.99       751491.49       3334126.5
#Sta/Elev= 30
       0843.8449 29.4351841.1221   58.87838.8349  98.117834.4659 147.176829.8339
156.9879828.7031166.7991826.8791176.6109824.6191 186.423 823.113  225.67821.5479
 304.163 818.962353.3449818.0841 426.129 817.174 452.695816.1401  462.63816.1468
473.6141 816.497  601.72821.1221631.5319821.8148760.7869823.7891770.7288824.1649
780.6721 824.936800.5569827.1769820.4421 828.785830.3849830.3721850.2701 836.854
870.1561841.0371880.0981843.8269 890.041846.9349909.9261 852.777 949.697865.8871
#Mann= 3 , 0 , 0
       0     .05       0 426.129     .03       0473.6141     .05       0
Bank Sta=426.129,473.6141
XS Rating Curve= 0 ,0
Exp/Cntr=0.3,0.1

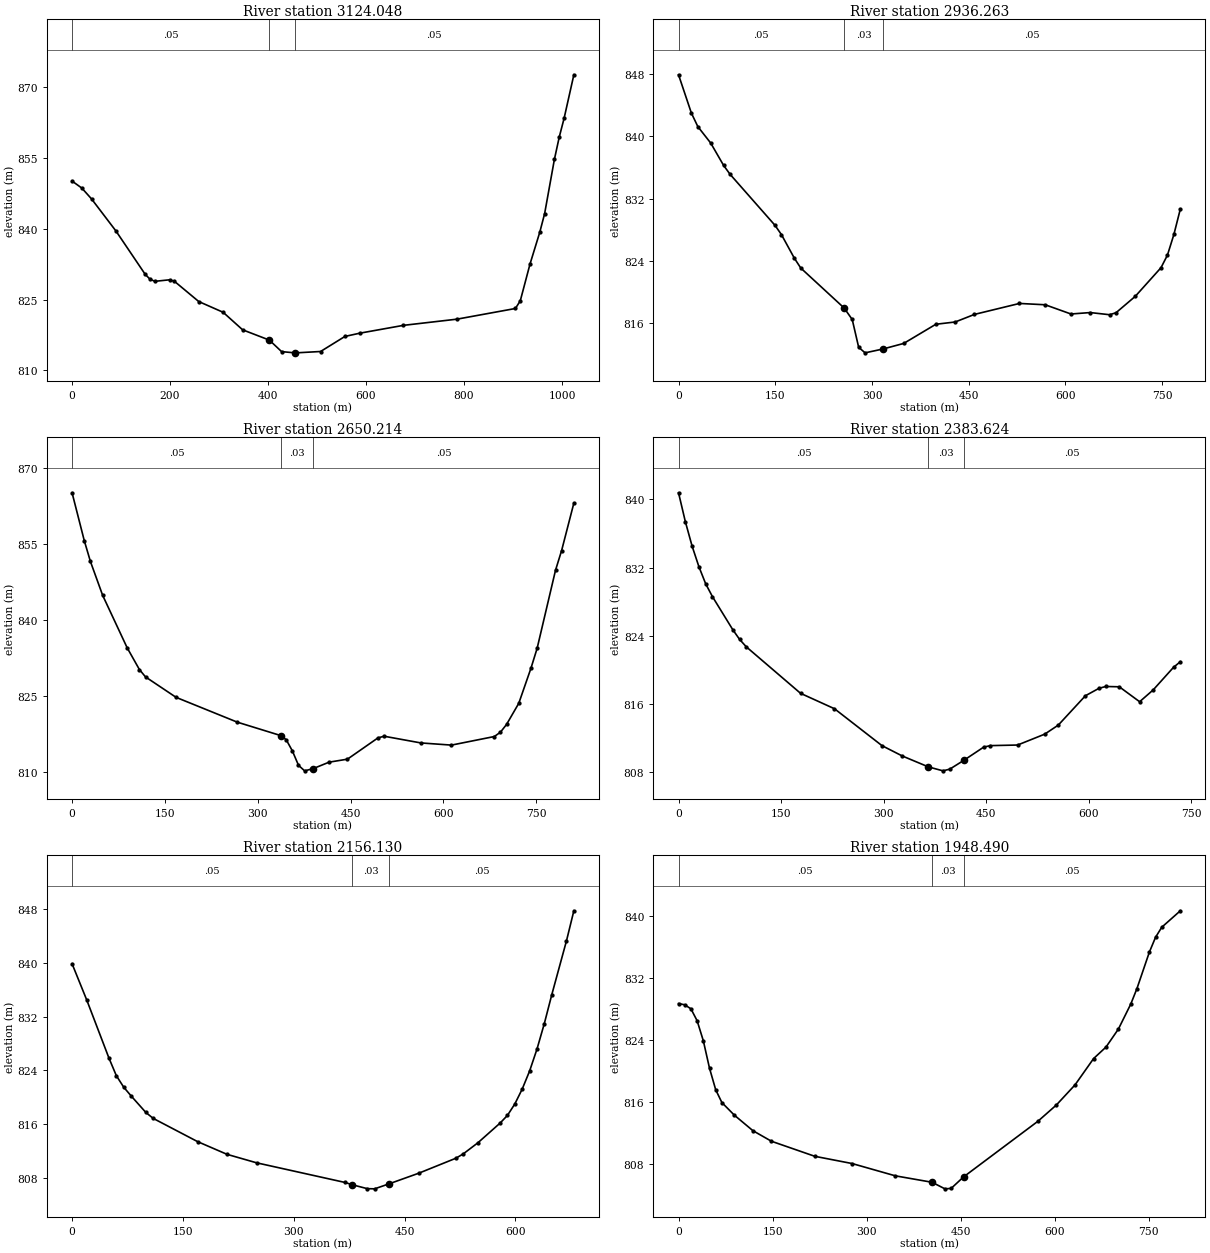
Type RM Length L Ch R = 1 ,3124.048,187.7852,187.7852,187.7852
XS GIS Cut Line= 3
       752090.39      3334869.43       752039.74      3334384.67
       751714.16       3333957.8
#Sta/Elev= 30
       0 850.118  19.894848.6379  39.788846.3351 89.5219839.5499149.2029830.3721
159.1501829.3239 169.097828.8828198.9381829.2042208.8849828.8911258.6188 824.598
308.3531822.3229 348.141818.6111402.7411816.4291427.7161813.9901 454.262813.7361
 457.556813.7331507.2811814.0168556.9909 817.209586.8171817.8869676.2951819.5551
 785.658820.8669904.9619823.1279914.9042824.7571 934.788832.5529 954.672839.2751
 964.614843.2311984.4979  854.69994.4398859.44091004.382 863.4311024.266872.6351
#Mann= 3 , 0 , 0
       0     .05       0402.7411     .03       0 454.262     .05       0
Bank Sta=402.7411,454.262
XS Rating Curve= 0 ,0
Exp/Cntr=0.3,0.1

Type RM Length L Ch R = 1 ,2936.263,286.049,286.049,286.049
XS GIS Cut Line= 2
       752386.85      3334560.61       751887.62       3333963.7
#Sta/Elev= 30
       0 847.939 19.9531843.0048 29.9289841.2721  49.882 839.157 69.8339 836.288
  79.811 835.145149.6449 828.564 159.621 827.369179.5741 824.345189.5508 823.074
 256.791 817.932269.3609816.4532279.3379 812.876 289.314 812.163317.0201812.6572
349.1719813.3732399.0539815.8411428.9832816.1318 458.912817.1082 528.746818.5181
 568.652818.3469608.5569817.1609638.4862817.3449668.4151817.0679678.3909  817.32
708.3201 819.435748.2249823.1218758.2022824.7401 768.178 827.394778.1541 830.662
#Mann= 3 , 0 , 0
       0     .05       0 256.791     .03       0317.0201     .05       0
Bank Sta=256.791,317.0201
XS Rating Curve= 0 ,0
Exp/Cntr=0.3,0.1

Type RM Length L Ch R = 1 ,2650.214,266.5891,266.5891,266.5891
XS GIS Cut Line= 2
       752596.85      3334413.61       752068.68      3333798.62
#Sta/Elev= 30
       0865.1681 19.7721855.6979 29.6589851.6069 49.4309844.9221  88.976834.5839
108.7481830.2919118.6339828.8329168.0649 824.794266.9271819.9001337.9671817.2222
 346.016 816.423355.9019 814.229365.7881811.3931375.6739810.2931 389.201810.7159
 415.219 812.004444.8778812.5959494.3079816.8061 504.195 817.121563.5121815.7999
612.9431815.3711682.1461 817.064 692.032817.9158701.9182819.4481721.6899823.6251
741.4629830.5831751.3491834.4811 781.007 849.869790.8942853.7701810.6662 863.129
#Mann= 3 , 0 , 0
       0     .05       0337.9671     .03       0 389.201     .05       0
Bank Sta=337.9671,389.201
XS Rating Curve= 0 ,0
Exp/Cntr=0.3,0.1

Type RM Length L Ch R = 1 ,2383.624,227.4939,227.4939,227.4939
XS GIS Cut Line= 2
       752744.99      3334218.75       752289.17      3333643.55
#Sta/Elev= 30
       0 840.788  9.9179  837.41 19.8349834.5251 29.7531832.1149 39.6709 830.103
 49.5891  828.59 79.3419824.7068 89.2589823.5721  99.177822.6891178.5189 817.231
228.1071 815.422297.5311811.0898327.2839809.8731 365.561 808.589  386.79 808.129
396.7079 808.329417.0078  809.35446.2961 810.914 456.214811.0911495.8849811.1599
535.5562 812.438555.3911813.4981 595.062816.9469614.8972817.8198 624.815818.0369
644.6511818.0009674.4042816.2449 694.239 817.636723.9921820.2908  733.91 820.944
#Mann= 3 , 0 , 0
       0     .05       0 365.561     .03       0417.0078     .05       0
Bank Sta=365.561,417.0078
XS Rating Curve= 0 ,0
Exp/Cntr=0.3,0.1

Type RM Length L Ch R = 1 ,2156.130,207.6401,207.6401,207.6401
XS GIS Cut Line= 2
       752929.67      3334080.79       752502.79      3333552.62
#Sta/Elev= 30
       0 839.838 19.9742834.4281 49.9339825.8348 59.9209823.2279  69.908821.5189
 79.8951820.2281 99.8689817.7681 109.856816.8859169.7769813.4472209.7249811.5541
 249.672810.2989369.5151 807.379 378.874  807.05399.4752806.4621409.4619 806.434
429.1959807.1838469.3828808.7609519.3179 810.971 529.305 811.612 549.278813.2731
579.2392816.1879 589.226817.3362 599.213819.0299609.2001821.2391619.1869 823.911
 629.173827.1619639.1598830.9711649.1469835.2112 669.121843.2399679.1078847.7009
#Mann= 3 , 0 , 0
       0     .05       0 378.874     .03       0429.1959     .05       0
Bank Sta=378.874,429.1959
XS Rating Curve= 0 ,0
Exp/Cntr=0.3,0.1

Type RM Length L Ch R = 1 ,1948.490,232.6429,232.6429,232.6429
XS GIS Cut Line= 2
       753045.43      3334008.44        752647.5      3333313.86
#Sta/Elev= 30
       0828.7061  9.8831 828.547 19.7651828.0279 29.6479 826.493  39.531 823.914
  49.413 820.375 59.2961817.5949 69.1789815.9429  88.944 814.329118.5919 812.324
148.2401810.9579 217.419809.0181276.7151808.0891345.8931806.5008404.4909805.6711
424.9549 804.825434.8371804.8771454.6031806.3569 573.195 813.527602.8429815.6381
632.4911818.2219 662.139821.6171681.9041823.0969  701.67825.4149721.4351828.6369
731.3179 830.644 751.083835.3309760.9661837.2469770.8489 838.541800.4968840.6649
#Mann= 3 , 0 , 0
       0     .05       0404.4909     .03       0454.6031     .05       0
Bank Sta=404.4909,454.6031
XS Rating Curve= 0 ,0
Exp/Cntr=0.3,0.1