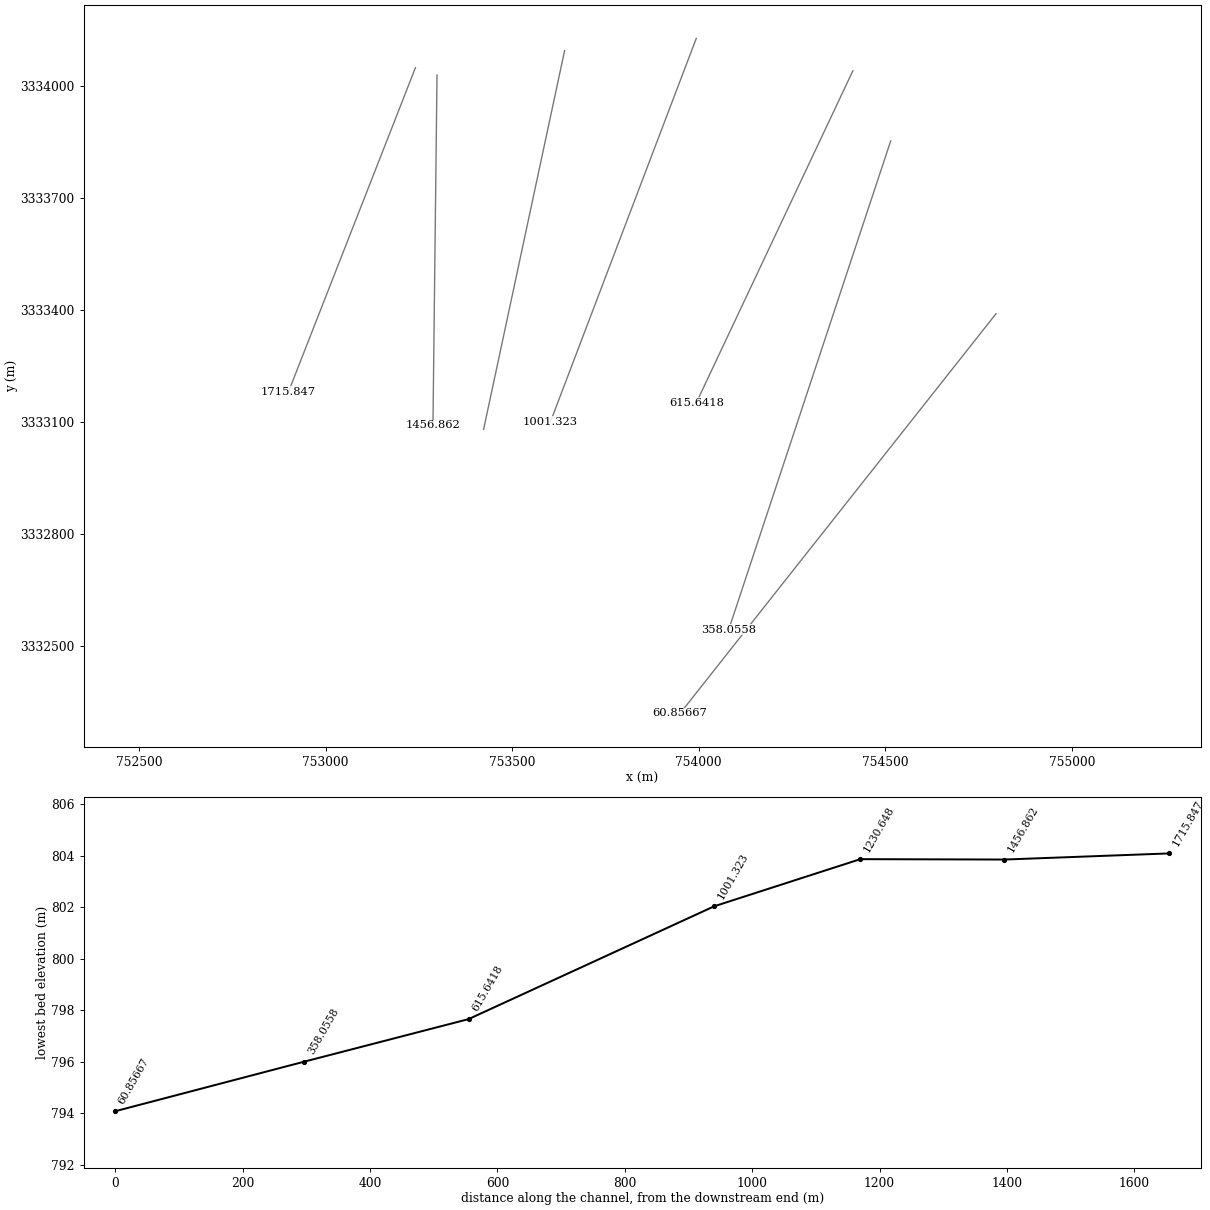
HEC-RAS study newStreamline.prj: newStreamline

--- newStreamline.g01 (geometry) --- (continued)

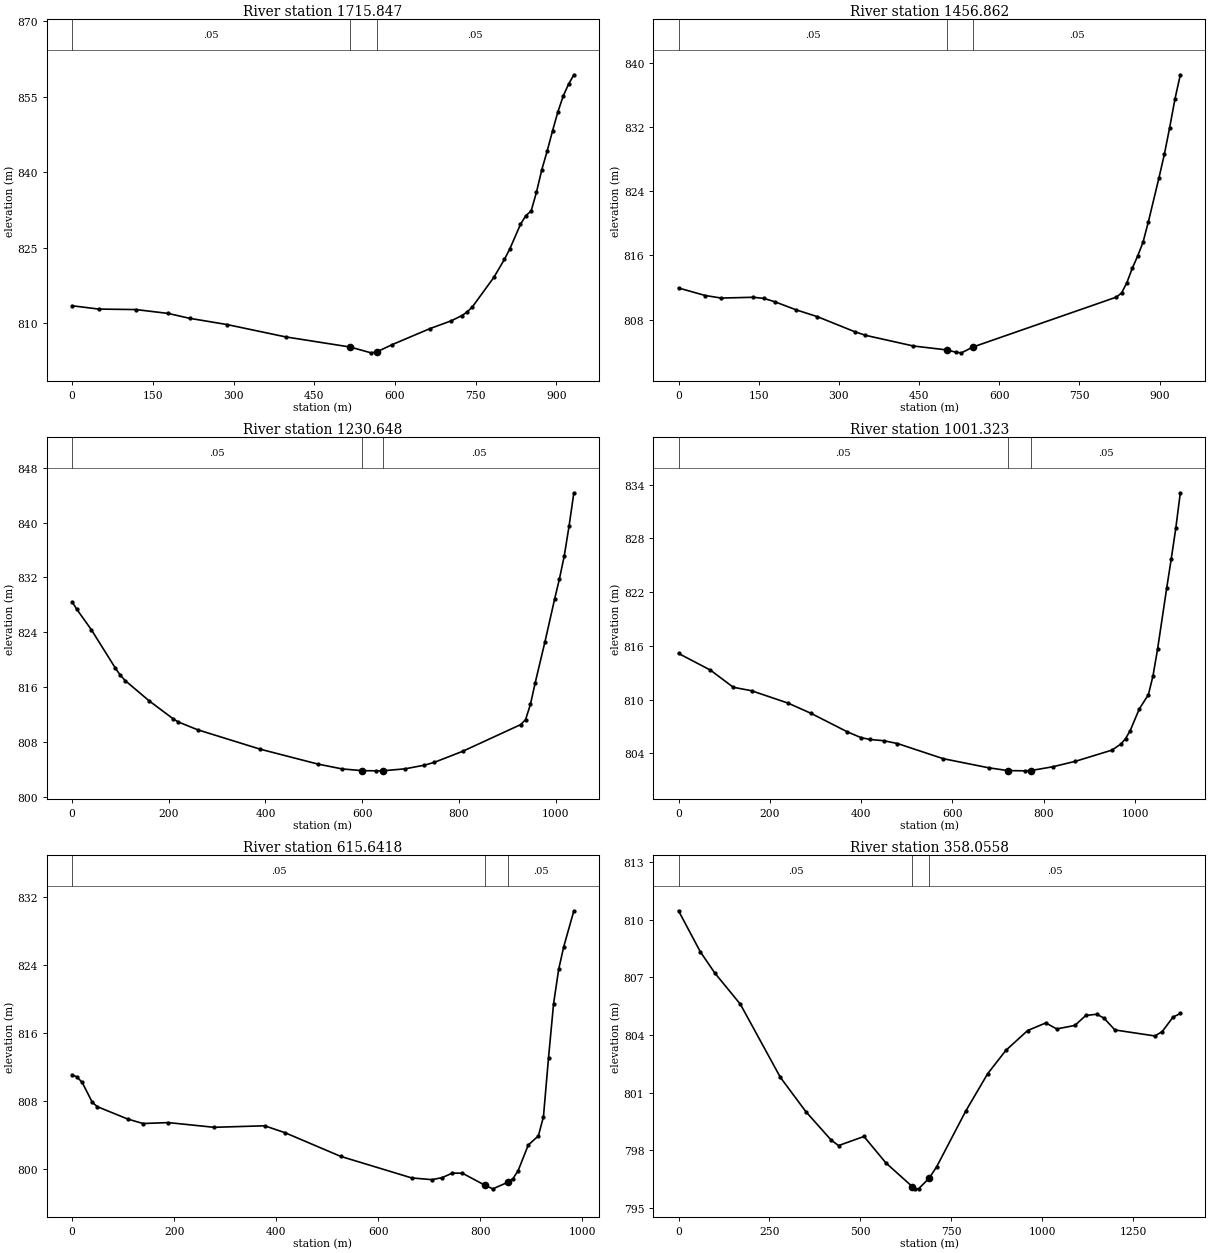
Type RM Length L Ch R = 1 ,1715.847,258.9849,258.9849,258.9849
XS GIS Cut Line= 2
       753240.78      3334048.64       752900.73      3333180.41
#Sta/Elev= 30
       0813.4539  49.598 812.794119.0351 812.694178.5531 811.926218.2319810.9591
 287.669809.7201 396.785807.2622516.9469805.2402 555.498 804.088 566.087 804.273
595.1769805.7369 664.614808.8911704.2932810.4471 724.132811.4861734.0519  812.21
743.9711813.2451  783.65819.0839 803.489822.6952813.4091824.7519833.2479829.6519
 843.167831.3731 853.087 832.311 863.007836.0621872.9258840.5439882.8459844.2189
 892.765 848.213 902.685851.9989 912.605855.1429922.5242857.5231932.4438859.4009
#Mann= 3 , 0 , 0
       0     .05       0516.9469     .03       0 566.087     .05       0
Bank Sta=516.9469,566.087
XS Rating Curve= 0 ,0
Exp/Cntr=0.3,0.1

Type RM Length L Ch R = 1 ,1456.862,226.214,226.214,226.214
XS GIS Cut Line= 2
       753298.49      3334028.82       753287.63      3333090.05
#Sta/Elev= 27
       0811.9299 49.9381810.9938    79.9 810.675139.8261 810.775159.8009 810.632
179.7759 810.223 219.726809.2142259.6771808.3601329.5891806.4849 349.565806.0369
439.4521804.7022501.9919804.2112 519.353  803.92529.3401  803.85 550.905804.5769
 818.979810.7881 828.967 811.316838.9541812.6138 848.942814.3909858.9301 815.899
868.9172817.6031878.9052820.1431898.8799825.6599908.8669828.5659918.8549831.9071
 928.842835.5001  938.83838.4969
#Mann= 3 , 0 , 0
       0     .05       0501.9919     .03       0 550.905     .05       0
Bank Sta=501.9919,550.905
XS Rating Curve= 0 ,0
Exp/Cntr=0.3,0.1

Type RM Length L Ch R = 1 ,1230.648,229.3251,229.3251,229.3251
XS GIS Cut Line= 2
       753640.35      3334093.94       753423.29       3333079.2
#Sta/Elev= 30
       0 828.476  9.9779827.3491 39.9111824.3981 89.7999818.7879 99.7781817.7839
 109.756 817.006159.6451814.0352209.5341811.4138219.5121810.9841259.4229809.8469
389.1351807.0141508.8682  804.84558.7569804.1401599.6821803.8969628.6022803.8649
642.9531803.8749688.4692804.1559728.3799804.6879748.3349805.0811808.2022  806.72
927.9349 810.601937.9132811.3301947.8911 813.541 957.869 816.715 977.824822.6149
997.7802828.82011007.758 831.7721017.735835.09591027.713839.45481037.691 844.328
#Mann= 3 , 0 , 0
       0     .05       0599.6821     .03       0642.9531     .05       0
Bank Sta=599.6821,642.9531
XS Rating Curve= 0 ,0
Exp/Cntr=0.3,0.1

Type RM Length L Ch R = 1 ,1001.323,385.6811,385.6811,385.6811
XS GIS Cut Line= 2
       753993.25       3334127.1       753602.54       3333099.7
#Sta/Elev= 30
       0 815.145 69.9479 813.282119.9111811.3682 159.881810.9802239.8209809.6009
 289.784 808.467369.7239 806.392399.7019805.7471 419.687805.5361449.6651805.3998
479.6421 805.085579.5681803.3961679.4931802.3751 721.282802.0659759.4342802.0361
 771.955802.0699819.3889 802.486869.3521803.1002 949.292804.3511969.2768 805.039
  979.27805.6348989.2631  806.521009.248808.94411029.233810.54491039.225812.6199
1049.218815.58811069.203822.40191079.195 825.6731089.188829.10781099.181 833.087
#Mann= 3 , 0 , 0
       0     .05       0 721.282     .03       0 771.955     .05       0
Bank Sta=721.282,771.955
XS Rating Curve= 0 ,0
Exp/Cntr=0.3,0.1

Type RM Length L Ch R = 1 ,615.6418,257.5859,257.5859,257.5859
XS GIS Cut Line= 2
       754412.89      3334040.28       753993.25      3333150.35
#Sta/Elev= 30
       0811.0811   9.938 810.811 19.8769810.1721 39.7542807.8301 49.6918 807.322
109.3229805.8659139.1391805.3441188.8309 805.452278.2769804.8991377.6618805.0759
 417.416804.2639526.7389801.4758665.8779798.9412705.6321798.7369725.5081798.9741
745.3851799.5029 765.262 799.499810.4462798.0499824.8931797.6561854.3279 798.423
864.6469798.8702874.5861799.7869894.4631802.8109  914.34803.8859 924.278 806.142
934.2159813.0759944.1552819.4469954.0929 823.483964.0318 826.144983.9091830.3809
#Mann= 3 , 0 , 0
       0     .05       0810.4462     .03       0854.3279     .05       0
Bank Sta=810.4462,854.3279
XS Rating Curve= 0 ,0
Exp/Cntr=0.3,0.1

Type RM Length L Ch R = 1 ,358.0558,297.1989,297.1989,297.1989
XS GIS Cut Line= 2
       754514.18      3333852.16       754080.07      3332542.59
#Sta/Elev= 30
       0 810.455 59.9849 808.321  99.975807.2158169.9571805.6011279.9289 801.802
 349.911800.0219 419.894 798.536 439.888798.2551 509.871798.7281 569.855797.3599
 643.192796.1151649.8351796.0071 659.832796.0099  688.72  796.55709.8188 797.159
 789.799800.0521849.7839801.9849899.7711 803.198959.7548804.23181009.743804.6269
1039.735 804.3161089.722804.49711119.714805.01491149.707805.07891169.702804.8798
1199.694804.26291309.666803.95121329.661 804.1741359.653804.93111379.648805.1179
#Mann= 3 , 0 , 0
       0     .05       0 643.192     .03       0  688.72     .05       0
Bank Sta=643.192,688.72
XS Rating Curve= 0 ,0
Exp/Cntr=0.3,0.1

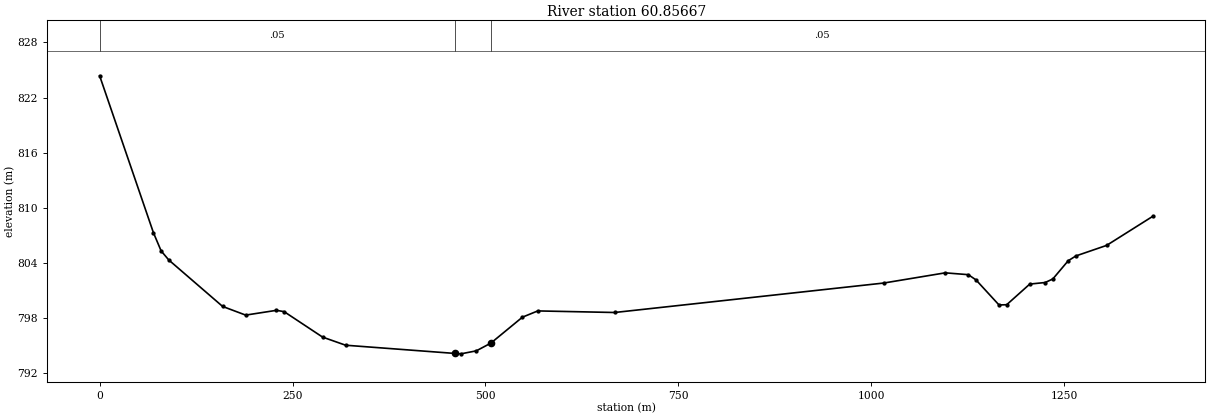
Type RM Length L Ch R = 1 ,60.85667,60.857,60.857,60.857
XS GIS Cut Line= 2
       754796.35      3333389.11       753949.83       3332318.3
#Sta/Elev= 30
       0824.3721 69.7449 807.272 79.7079805.2932 89.6719 804.301159.4159799.2429
 189.307798.2999229.1611798.8201239.1241798.6769288.9419 795.905318.8321 795.019
460.2782 794.125 468.285794.0802488.2119794.4061 507.097795.2491547.9929798.0749
567.9201798.7562 667.555798.58391016.277801.79281095.985802.90391125.876802.7051
1135.839802.1388 1165.73799.40291175.693799.43191205.584801.68011225.511801.8499
1235.474802.23691255.401804.22091265.365804.74521305.219805.8948    1365809.0608
#Mann= 3 , 0 , 0
       0     .05       0460.2782     .03       0 507.097     .05       0
Bank Sta=460.2782,507.097
XS Rating Curve= 0 ,0
Exp/Cntr=0.3,0.1

Chan Stop Cuts=-1
Use User Specified Reach Order=0
Composite Channel Slope=5